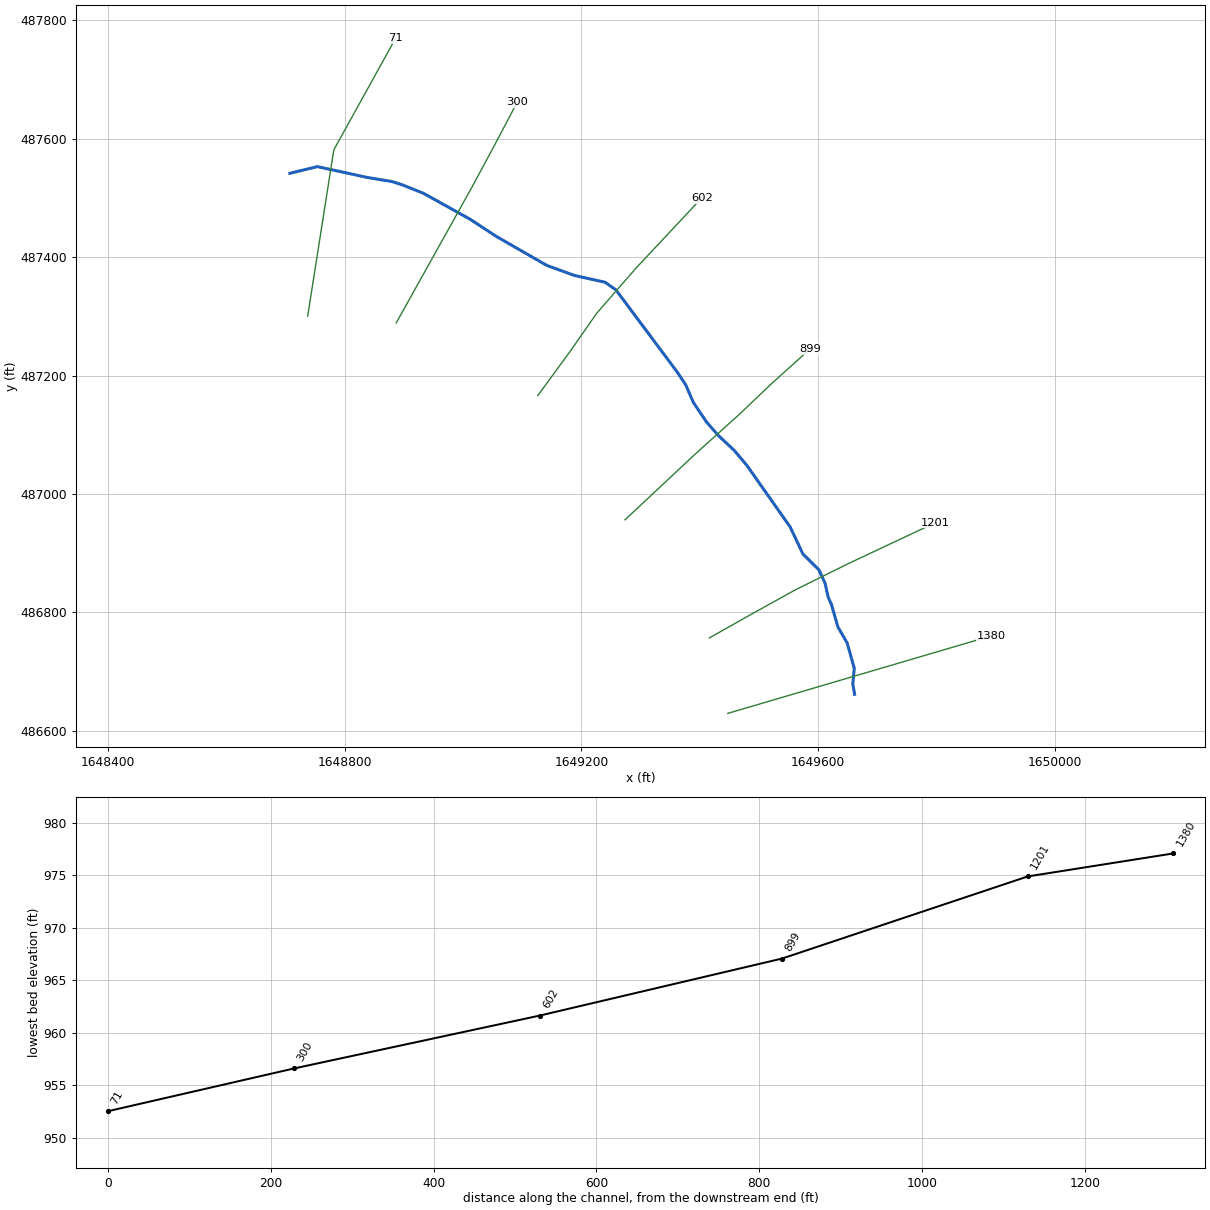
--- LaurelRnII.prj (project) ---

Proj Title=LaurelRnII
Current Plan=p01
Default Exp/Contr=0.3,0.1
English Units
Geom File=g01
Flow File=f01
Plan File=p01
Y Axis Title=Elevation
X Axis Title(PF)=Main Channel Distance
X Axis Title(XS)=Station
BEGIN DESCRIPTION:
---------- MODELED AS PART OF WVEM CTP PROGRAM, 2025----------
Stream Name: Laurel Run II
Flood Zone: AFH
Marshall County, WV
HEC-RAS Version: RAS 6.6
Vertical Datum: NAVD88
Projection: NAD 1983 StatePlane West Virginia N FIPS 4701 (US Feet)
Terrain: 1-meter West Virginia FEMA R3 South Central (collected 2018-2019)
Land Use: 2024 NLCD
Hydrologic Method:
Duda et al., "Estimation of magnitude and frequency of floods for rural, unregulated streams in and near Virginia and West Virginia." September 8, 2025.
Additional Model Notes:
None
END DESCRIPTION:
DSS Export Rating Curves= 0
DSS Export Rating Curve Sorted= 0
DSS Export Volume Flow Curves= 0
DXF OffsetX= 0
DXF OffsetY= 0
DXF ScaleX= 1
DXF ScaleY= 10

--- LaurelRnII.p01 (plan) ---

Plan Title=Floodplain
Program Version=6.60
Short Identifier=Floodplain
Geom File=g01
Flow File=f01
Subcritical Flow
K Sum by GR= 0
Std Step Tol= 0.01
Critical Tol= 0.01
Num of Std Step Trials= 20
Max Error Tol= 0.3
Flow Tol Ratio= 0.001
Split Flow NTrial= 30
Split Flow Tol= 0.02
Split Flow Ratio= 0.02
Log Output Level= 0
Friction Slope Method= 1
Unsteady Friction Slope Method= 2
Unsteady Bridges Friction Slope Method= 1
Parabolic Critical Depth
Global Vel Dist= 0 , 0 , 0
Global Log Level= 0
CheckData=True
Encroach Param=-1 ,0,0, 0
Flow Ratio Tolerance=0.1
Flow Ratio Min Ratio=0.5
Flow Ratio Max Ratio=4
Flow Ratio Max Iterations= 10
Computation Interval=1MIN
Output Interval=1HOUR
Instantaneous Interval=1HOUR
Mapping Interval=1HOUR
Computation Time Step Use Courant=        0
Computation Time Step Use Time Series=    0
Computation Time Step Count To Double=0
Computation Time Step Max Doubling=0
Computation Time Step Max Halving=0
Computation Time Step Residence Courant=0
Run HTab= 0
Run UNet= 0
Run Sediment= 0
Run PostProcess= 0
Run WQNet= 0
Run RASMapper=-1
UNET Theta= 1
UNET Theta Warmup= 1
UNET ZTol= 0.02
UNET ZSATol= 0.02
UNET MxIter= 20
UNET Max Iter WO Improvement= 0
UNET MaxInSteps= 0
UNET DtIC= 0
UNET DtMin= 0
UNET MaxCRTS= 20
UNET WFStab= 2
UNET SFStab= 1
UNET WFX= 1
UNET SFX= 1
UNET Gravity=32.17405
UNET 1D Methodology=Finite Difference
UNET DSS MLevel= 4
UNET Pardiso=0
UNET DZMax Abort= 100
UNET Use Existing IB Tables=-1
UNET Froude Reduction=False
UNET Froude Limit= 0.8
UNET Froude Power= 4
UNET D1 Cores= 0
UNET WindReference=Eulerian
UNET WindDragFormulation=Hsu (1988)
UNET D2 Coriolis=0
UNET D2 Cores= 0
UNET D2 Theta= 1
UNET D2 Theta Warmup= 1
UNET D2 Z Tol= 0.01
UNET D2 Volume Tol= 0.01
UNET D2 Max Iterations= 20
UNET D2 Advanced Convergence=0
UNET D2 WS Max Tol=0.15
UNET D2 WS RMS Tol=0.002
UNET D2 WS Stall Tol=1
UNET D2 Equation= 0
UNET D2 RampUpFraction=0.1
UNET D2 TimeSlices= 1
UNET D2 Turbulence Formulation=None
UNET D2 Eddy Viscosity=0.3
UNET D2 Transverse Eddy Viscosity=0.1
UNET D2 Smagorinsky Mixing=0.05
UNET D2 BCVolumeCheck=0
UNET D2 Cores=0
UNET D2 SolverType=PARDISO (Direct)
UNET D2 Minimum Iterations= 3
UNET D2 Maximum Iterations= 30
UNET D2 Restart Number= 10
UNET D2 Relaxation Coeff=1.3
UNET D2 SOR Precondition Iterations= 10
UNET D2 ILUT Maximum Fill= 8
UNET D2 ILUT Tolerance=1E-08
UNET D2 Convergence Tolerance=0.00001
PS Theta= 1
PS WS Tol= 0.01
PS Volume Tol= 0.01
PS Max Iterations= 20
PS Equation= 0
PS Advance Time Step=-1
PS Target Courant=0.9
PS Time Slices= 1
PS Iterate With 2D=0
PS Project Initial WSE from DS=-1
PS Ramp Up Initial WSE from US=-1
PS Cores=0
UNET D1D2 MaxIter= 0
UNET D1D2 ZTol=0.01
UNET D1D2 QTol=0.1
UNET D1D2 MinQTol=1
Write IC File= 0
Write IC File at Fixed DateTime=0
Write IC File at Sim End=0
Echo Input=False
Echo Parameters=False
Echo Output=False
Write Detailed= 0
HDF Write Warmup=0
HDF Write Time Slices=0
HDF Flush=0
HDF Compression= 1
HDF Chunk Size= 1
HDF Spatial Parts= 1
HDF Use Max Rows=0
HDF Fixed Rows= 1
Calibration Method= 0
Calibration Iterations= 20
Calibration Max Change=0.05
Calibration Tolerance=0.2
Calibration Maximum=1.5
Calibration Minimum=0.5
Calibration Optimization Method= 1
WQ AD Non Conservative
WQ ULTIMATE=-1
WQ Max Comp Step=1HOUR
WQ Output Interval=15MIN
WQ Output Selected Increments= 0
WQ Create Restart=0
WQ Fixed Restart=0
WQ System Summary=0
WQ Write To DSS=0
Sorting and Armoring Iterations= 10
XS Update Threshold= 0.02
Bed Roughness Predictor= 0
Processes Affected by Predictor=Sediment Only
Hydraulics Update Threshold= 0.02
Energy Slope Method= 1
Volume Change Method= 1
Sediment Retention Method= 0
Sediment TS Multiplier= 1
Warm Up Method= 0
XS Weighting Method= 0
Number of US Weighted Cross Sections= 1
Number of DS Weighted Cross Sections= 1
Upstream XS Weight=0
Main XS Weight=1
Downstream XS Weight=0
Number of DS XS's Weighted with US Boundary= 1
Upstream Boundary Weight= 1
Weight of XSs Associated with US Boundary= 0
Number of US XS's Weighted with DS Boundary= 1
Downstream Boundary Weight= 0.5
Weight of XSs Associated with DS Boundary= 0.5
Percentile Method= 0
Sediment Output Level= 3
Mass or Volume Output= 0
Output Increment Type= 1
Profile and TS Output Increment= 1
Transport Output Increment 1
XS Output Flag= 0
XS Output Increment= 10
Read HDF5 Sediment Hotstart= 0
Sediment Hotstart Type= 0
Write Gradation File= 0
Read Gradation Hotstart= 0
Write HDF5 File= 1
Write Binary Output= 1
Write DSS Sediment File= 0
DSS Sediment Output Type= 1
SV Curve= 0
Specific Gage Flag= 0
Subcell Erosion Methods= 0
Subcell Deposition Methods= 0
Advection Scheme= 1
Matrix Solver= 0
Implicit Weighting Factor= 1
Maximum Outer Loop Convergence Iterations= 5
Convergence Maximum Absolute= 0.001
Convergence RMSE= 0.0001
Grain Fractions Max Abs Error= 0.001
Max Subgrid Regions= 1
Max Subgrid Length Scale= 3.402823E+38
Initial Layer Thickness= 3
Min Layer Thickness= 0.1
Max Layer Thickness= 6
Number of Layers= 5

--- LaurelRnII.f01 (steady flow) ---

Flow Title=Flow
Program Version=6.60
Number of Profiles= 1
Profile Names=P100yr
River Rch & RM=LaurelRnII,Main            ,1380
     686
Boundary for River Rch & Prof#=LaurelRnII,Main            , 1
Up Type= 0
Dn Type= 3
Dn Slope=0.014
DSS Import GetInterval= 0
DSS Import GetPeak= 0
DSS Import FillOption= 0

--- LaurelRnII.g01 (geometry) ---

Geom Title=Geometry
Program Version=6.60

River Reach=LaurelRnII      ,Main
Reach XY= 30
1649661.40953456486661.4777621481649658.40757206486679.083698064
1649660.81275097486705.5413223061649648.78685638486748.354228809
1649633.23964339486775.2347524761649622.15633222486813.718271315
 1649616.9224188486825.1093246491649611.50805956486849.022990733
1649601.18622981486871.731606722 1649574.1193548486898.568823397
1649552.55771814486944.2153856461649479.34067297 487048.37167339
1649458.06053181487073.5720823111649431.18000814487098.772491232
1649411.57965364487121.1727088991649389.17943597487154.213325232
1649376.29921238487183.893712059 1649362.2989123487205.173853233
1649258.24957973487344.6834167241649239.97074489487357.585949972
1649188.36028381487369.0547590551649141.76752922487385.899869725
1649055.03345072487435.7183396371649012.02500655 487464.03225939
1648933.23316939487507.8008726391648897.67910664487522.022300899
1648880.01706848 487527.756869481648838.26977664487534.638089314
1648753.70925023487552.9848373981648707.41275489487541.604938895

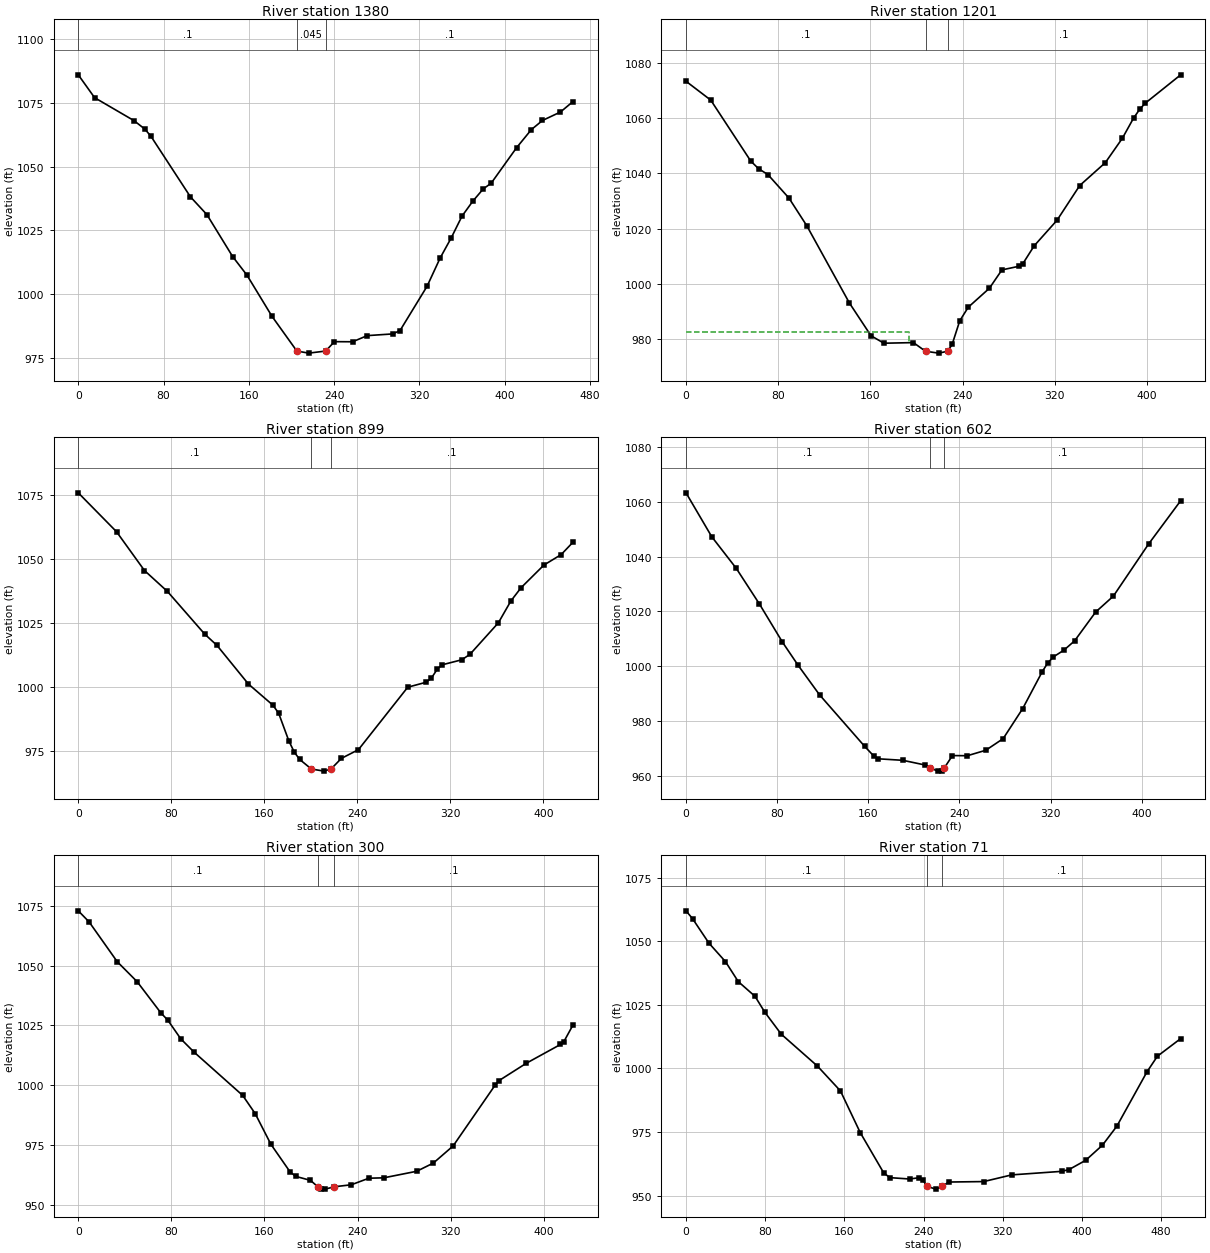
Type RM Length L Ch R = 1 ,1380    ,176.8,178.9,179.8
XS GIS Cut Line= 2
1649447.14110626486629.3479726051649892.38085216486760.300839047
#Sta/Elev= 30
       0 1085.83    15.3 1076.91    52.3 1067.92    62.5 1064.61    68.2  1061.8
   105.2 1038.16   120.7 1031.19   144.8 1014.83   158.3 1007.52   181.8  991.42
  205.08977.8798   216.2  977.07   232.1977.8807   240.3  981.55   257.4  981.51
   271.1  983.91   295.1  984.58   301.9  985.91   327.2 1003.17   339.5 1014.24
   349.8 1022.03     360  1030.6   370.3 1036.53     380 1041.27   387.4 1043.48
   411.3  1057.4   425.1 1064.43   435.5 1067.99   452.4  1071.3464.0981 1075.37
#Mann= 3 ,-1,0
       0      .1       0  205.08    .045       0   232.1      .1       0
Bank Sta=205.08,232.1
XS Rating Curve= 0 ,0
Exp/Cntr(USF)=0,0
Exp/Cntr=0.3,0.1

Type RM Length L Ch R = 1 ,1201    ,298.2,301.7,303.4
XS GIS Cut Line= 6
1649416.19972317486756.9217970071649493.97384584486800.720922008
1649561.27686083486838.0029996781649651.34196943486882.576729417
1649719.20403843486914.5103925911649798.37645225486951.766223595
#Sta/Elev= 30
       0 1073.33    21.5 1066.49    56.2 1044.42    62.9 1041.69    71.1 1039.52
    89.3 1031.04   104.8    1021   141.8  993.01   160.5  981.18   171.7  978.47
   197.3  978.69  207.82975.5516   219.2  974.88  226.98  975.55   230.9  978.04
   237.5  986.58   244.9  991.51   263.2  998.36   274.1 1005.02   288.6 1006.31
   292.3  1007.3   302.1 1013.75   321.9    1023   341.6 1035.57   363.8 1043.85
   378.6 1052.69   388.4 1060.06   393.7  1063.2   398.3 1065.34  429.19 1075.66
#Mann= 3 ,-1,0
       0      .1       0  207.82    .045       0  226.98      .1       0
#XS Ineff= 2 , 0
          193.14  982.46
Permanent Ineff=
       F       F
Bank Sta=207.82,226.98
XS Rating Curve= 0 ,0
Exp/Cntr(USF)=0,0
Exp/Cntr=0.3,0.1

Type RM Length L Ch R = 1 ,899     ,297.1,297.4,298
XS GIS Cut Line= 6
1649273.61273801486956.3403614161649337.45480192487016.134533167
1649392.19156909487067.4008348441649466.50080368487134.335412249
1649520.84190235487186.125991091  1649586.123924487244.828301504
#Sta/Elev= 30
       0 1075.92    32.9  1060.7    56.9 1045.54    76.7 1037.33   108.7 1020.67
   119.3 1016.23   146.3 1001.13   167.4  992.85   172.3  989.71   181.1  978.84
   185.8  974.45   190.4  971.63  200.43967.8959   211.3  967.07  217.32967.8957
   226.2  972.04   240.9  975.47   283.3  999.89   298.6 1001.77   303.4 1003.31
   308.8 1007.01   312.9 1008.66   329.7 1010.61   336.7 1012.71   361.2 1025.07
     372 1033.64   380.8 1038.84   400.4 1047.68   415.2 1051.76425.3386 1056.59
#Mann= 3 ,-1,0
       0      .1       0  200.43    .045       0  217.32      .1       0
Bank Sta=200.43,217.32
XS Rating Curve= 0 ,0
Exp/Cntr(USF)=0,0
Exp/Cntr=0.3,0.1

Type RM Length L Ch R = 1 ,602     ,300,301.8,302.5
XS GIS Cut Line= 6
1649126.31677276 487166.374390171649180.65163784487240.569451749
1649225.57477634487305.0345459281649292.08973518487381.443841919
1649343.33503951487436.1582994161649403.11904067487499.989208505
#Sta/Elev= 30
       0 1063.32    22.6 1047.28    44.1 1035.74    64.4 1022.74    84.7 1008.75
    98.4 1000.32   117.2  989.54   156.8  970.71   164.8  967.19   168.8  966.15
   190.4   965.6   209.6  963.91  214.47 962.827   220.9  961.65   224.9  961.87
  226.76962.8258   233.9  967.33     247  967.28   263.2  969.28   278.4  973.51
   295.6  984.52   312.8  998.04   317.6 1001.19   322.5 1003.38   331.8 1005.86
   341.1 1009.23   359.6 1019.76   375.2  1025.6   406.1 1044.63434.2621 1060.44
#Mann= 3 ,-1,0
       0      .1       0  214.47    .045       0  226.76      .1       0
Bank Sta=214.47,226.76
XS Rating Curve= 0 ,0
Exp/Cntr(USF)=0,0
Exp/Cntr=0.3,0.1

Type RM Length L Ch R = 1 ,300     ,226.4,228.8,231.5
XS GIS Cut Line= 6
1648887.11416717487288.989630505 1648929.7338326487365.408440918
1648966.26558368487430.9099503461649014.97250725487518.246061757
 1649050.5721736487584.267583251  1649091.388693487661.691641003
#Sta/Elev= 30
       0 1072.87     9.3 1068.25    33.5 1051.61    50.6 1043.26      71 1030.22
    76.9 1027.22    88.1 1019.38    99.4 1013.89   141.3  995.75     152  988.17
   165.5  975.36   181.9  963.88   186.8  961.95   199.5  960.28  205.83957.6141
   208.3   956.8   212.1  956.62  220.08957.6133   234.6  958.44   249.7  961.18
   262.5  961.34   290.8  964.08   305.1  967.51   322.1  974.67   358.4 1000.22
   361.5 1001.95   385.1 1009.24   414.3 1017.04   417.1 1018.12 425.032 1025.15
#Mann= 3 ,-1,0
       0      .1       0  205.83    .045       0  220.08      .1       0
Bank Sta=205.83,220.08
XS Rating Curve= 0 ,0
Exp/Cntr(USF)=0,0
Exp/Cntr=0.3,0.1

Type RM Length L Ch R = 1 ,71      ,,,
XS GIS Cut Line= 3
1648737.51276112 487300.41331763  1648781.638639487581.291501804
1648886.01331167487769.675057353
#Sta/Elev= 30
       0 1061.96     6.6 1058.88    23.2 1049.24    39.8 1042.02    52.8 1034.13
    69.7 1028.35    79.6 1022.11    96.2 1013.47   132.8 1000.91     156  991.16
     176  974.77   199.6     959   205.8  957.07   225.8  956.53   235.7  957.04
   239.1  956.14  243.87953.6049   252.3  952.55  258.43953.6057   265.6  955.34
   300.7  955.52     329  958.15   379.5  959.54     387  960.26   403.8   963.9
   420.7  969.84   435.2  977.29   465.7   998.7   476.2 1004.81 499.689 1011.73
#Mann= 3 ,-1,0
       0      .1       0  243.87    .045       0  258.43      .1       0
Bank Sta=243.87,258.43
XS Rating Curve= 0 ,0
Exp/Cntr(USF)=0,0
Exp/Cntr=0.3,0.1
LCMann Table=0

Chan Stop Cuts=-1
Use User Specified Reach Order=0
Composite Channel Slope=5